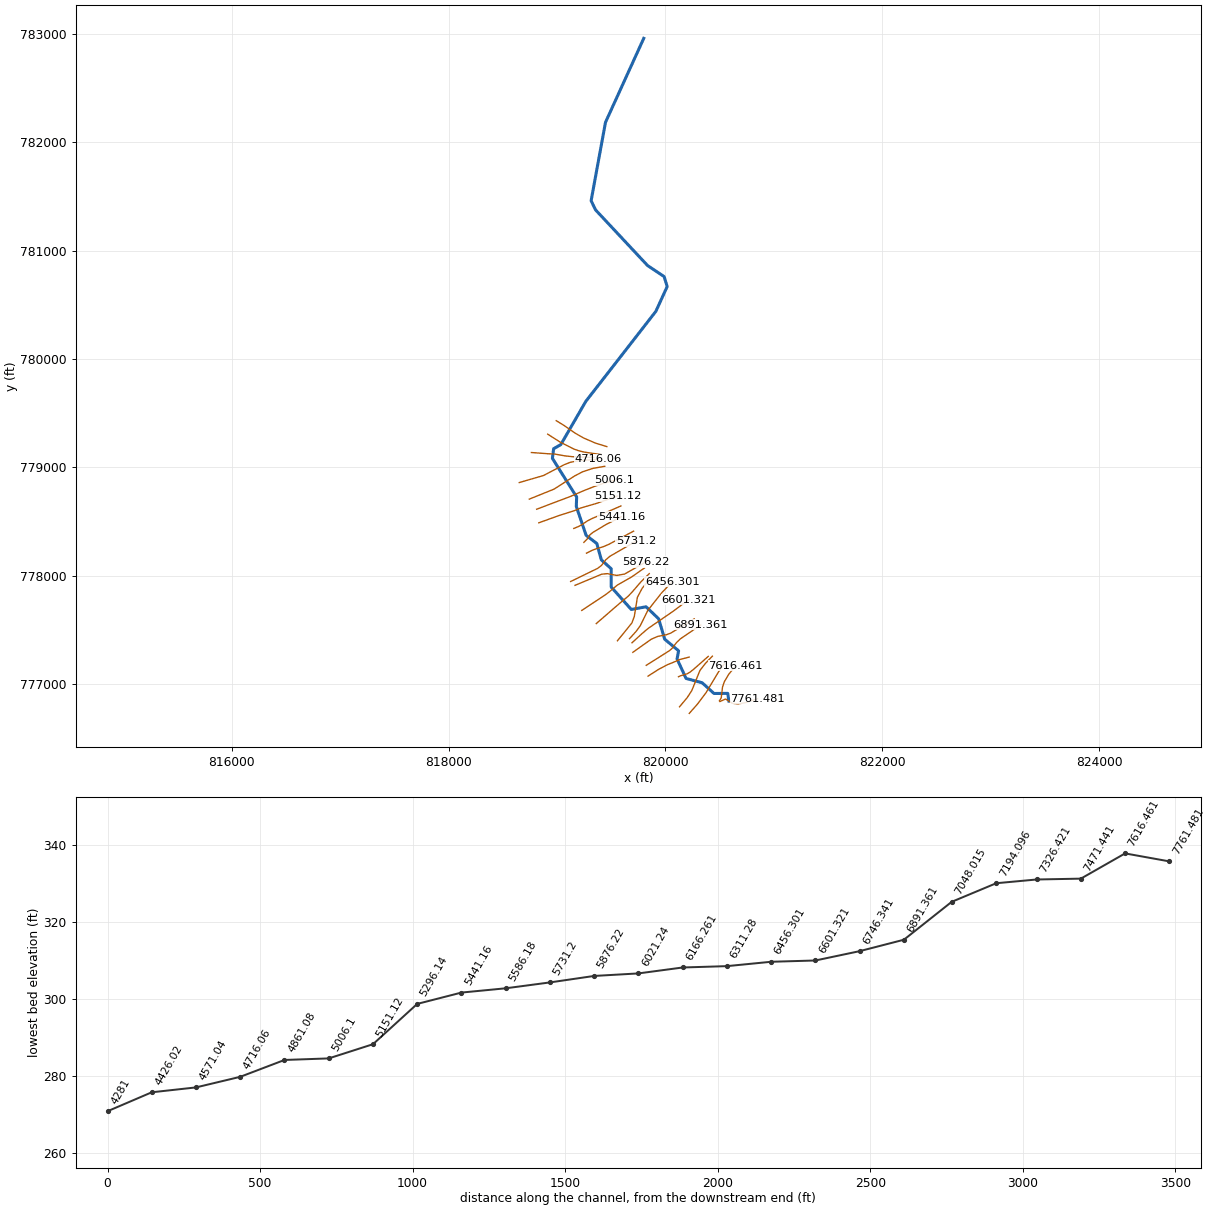
--- 17371_ras.prj (project) ---

Proj Title=17371
Current Plan=p01
Default Exp/Contr=0.3,0.1
English Units
Geom File=g01
Flow File=f01
Plan File=p01
Y Axis Title=Elevation
X Axis Title(PF)=Main Channel Distance
X Axis Title(XS)=Station
BEGIN DESCRIPTION:
RFD model 17371 exported to HEC-RAS
END DESCRIPTION:

--- 17371_ras.p01 (plan) ---

Plan Title=Plan 01
Program Version=4.10
Short Identifier=Plan 01
Geom File=g01
Flow File=f01
Subcritical Flow
Calc Critical at every XS
Secant Critical Depth

--- 17371_ras.f01 (steady flow) ---

Flow Title=Flow 01
Program Version=5.01
Number of Profiles= 6
Profile Names=10yr,25yr,50yr,100yr,100plus,500yr
River Rch & RM=17371,25,7761.481
   319.4   499.5  664.69  810.53 1183.38 1833.48
River Rch & RM=17371,25,7616.461
  320.57  501.36  667.18  813.58 1187.82 1839.45
River Rch & RM=17371,25,7471.441
  322.51  504.42  671.29  818.62 1195.19 1849.39
River Rch & RM=17371,25,7326.421
  324.05  506.86  674.57  822.65 1201.06 1857.32
River Rch & RM=17371,25,7194.096
  325.55  509.26   677.8  826.63 1206.88 1865.24
River Rch & RM=17371,25,7048.015
  363.61  569.86  759.45  927.17 1353.67 2062.99
River Rch & RM=17371,25,6891.361
  368.28  577.35  769.59   939.7 1371.97 2087.65
River Rch & RM=17371,25,6746.341
  382.83  600.57  800.92  978.32 1428.35 2162.82
River Rch & RM=17371,25,6601.321
  387.81  608.55  811.72  991.67 1447.84 2188.89
River Rch & RM=17371,25,6456.301
  389.58  611.39  815.57  996.43 1454.79 2198.17
River Rch & RM=17371,25, 6311.28
  393.84  618.21  824.79 1007.84 1471.44 2220.38
River Rch & RM=17371,25,6166.261
  397.02  623.31   831.7 1016.37  1483.9 2236.99
River Rch & RM=17371,25, 6021.24
   414.8  651.72  870.09 1063.74 1553.07 2328.36
River Rch & RM=17371,25, 5876.22
  420.74  661.25  882.98 1079.68 1576.33  2359.1
River Rch & RM=17371,25,  5731.2
  424.92  667.95  892.06  1090.9 1592.72 2380.71
River Rch & RM=17371,25, 5586.18
  426.66  670.74  895.84 1095.57 1599.53 2389.69
River Rch & RM=17371,25, 5441.16
  429.44   675.2  901.87 1103.03 1610.43 2404.03
River Rch & RM=17371,25, 5296.14
  460.29  724.59  968.69 1185.56 1730.91 2561.39
Boundary for River Rch & Prof#=17371,25,1
Up Type= 0
Dn Type= 2
Boundary for River Rch & Prof#=17371,25,2
Up Type= 0
Dn Type= 2
Boundary for River Rch & Prof#=17371,25,2
Up Type= 0
Dn Type= 2
Boundary for River Rch & Prof#=17371,25,2
Up Type= 0
Dn Type= 2
Boundary for River Rch & Prof#=17371,25,2
Up Type= 0
Dn Type= 2
Boundary for River Rch & Prof#=17371,25,2
Up Type= 0
Dn Type= 2

--- 17371_ras.g01 (geometry) ---

Geom Title=17371
Program Version=4.10

River Reach=17371,25
Reach XY= 30
820584.764446557776844.455444684820574.159544497776915.797512983
820447.382761063776914.833430968820337.959453583 777013.65183634
820189.972866032777053.179198524820106.579772684 777233.46253323
820121.041002751777308.178888501819992.567170622777415.355608648
819936.749763728777603.997672023819820.729458601777714.539453084
819684.282312751777689.737042932 819499.23187968777896.843726774
819498.951875418778065.701510499819407.967993348 778147.48077474
819366.628908814778298.153693252819267.688842326778373.903916653
819177.417046668 778639.43400668819180.259249124778727.542280968
818956.672660591779083.764981244 818968.04147017779172.820656295
819034.359526068779210.716688272819264.937045011779609.692867508
819911.087194921780439.997219058 820015.64894998780668.699909846
819987.497057261780760.563808126819834.647088975780862.565960763
819354.683222622781375.982447511 819313.86291978781460.466648139
819446.339864552782183.177340352819799.401397112782958.512662087

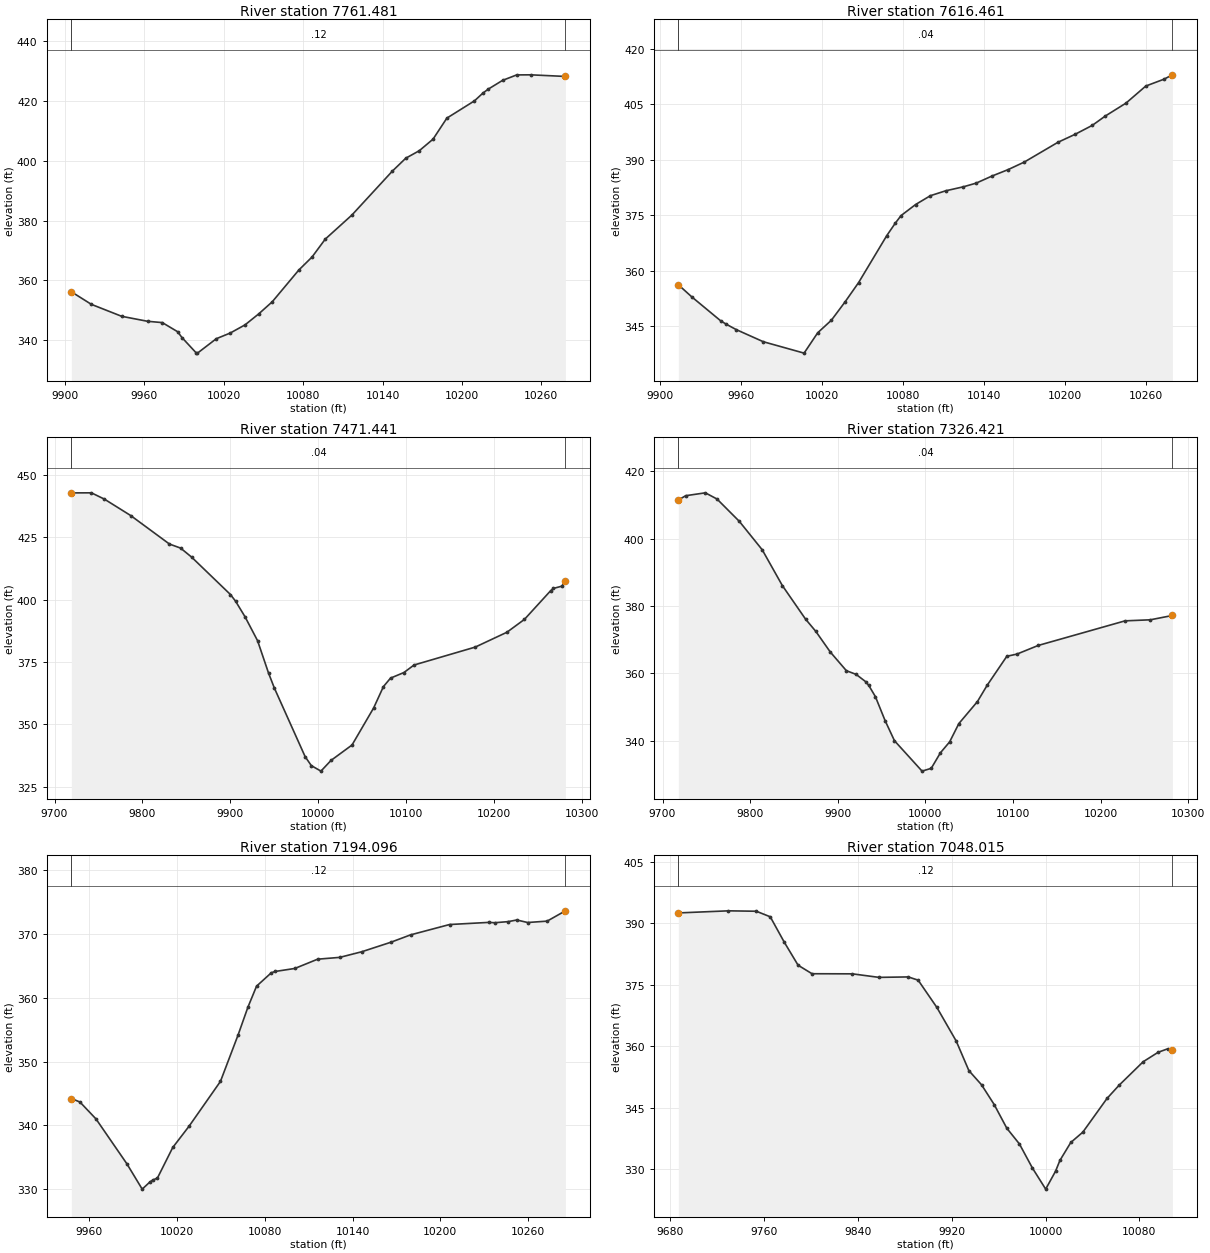
Type RM Length L Ch R = 1 ,7761.481,145.020000,145.020000,145.020000
XS GIS Cut Line= 6
820502.781464256776840.606376785820554.161444832776863.840223938
820615.284732424776824.869783529  820667.1179233776818.576085833
820744.610425743776830.944038736 820849.55007935776866.704229534
#Sta/Elev= 30
9904.696356.20669919.818352.00249942.743 348.0029962.293346.33579973.474345.8972
9985.026342.84999988.345340.8904    9999335.807610000.07 335.68310014.29340.5019
10024.87342.412610036.06345.146710046.34348.797510056.58352.841210076.67363.4683
10086.68367.826710096.72373.8357 10116.8381.859810147.36396.538210157.57400.8889
 10167.8403.401910178.23 407.28110188.66414.303610209.53420.082510215.99422.7068
10220.12424.053210230.79426.938410241.46428.761910252.12428.791910278.31428.2491
#Mann= 3 , 0 , 0
9904.696    0.12       09904.696    0.12       010278.31    0.12       0
#XS Ineff= 2 , 0
       0                               0
Bank Sta=9904.696,10278.31
Exp/Cntr=0.3,0.1

Type RM Length L Ch R = 1 ,7616.461,145.020000,145.020000,145.020000
XS GIS Cut Line= 6
820497.767136626776847.225289257820514.029685491776873.825775768
820526.239155975776975.422685944820542.096516295777022.025225052
820584.255365218777093.517946055820648.067048983777169.580336237
#Sta/Elev= 30
9913.762356.23799923.637352.98259945.099346.48489949.222345.57119956.596 344.111
9976.677340.8296 10006.8337.752810016.89343.260810026.99346.647810037.08351.5836
10047.18356.850910067.99369.531910074.26372.882410078.54374.943310089.32377.9381
10100.25380.323210111.54381.643210124.69382.730110134.12  383.7210145.86385.6405
10157.83387.3859 10169.8389.429610194.61394.757510207.35396.924810220.08399.3457
10229.66401.859110244.98405.353110259.66409.976510273.16411.833410279.34413.0091
#Mann= 3 , 0 , 0
9913.762    0.04       09913.762    0.04       010279.34    0.04       0
#XS Ineff= 2 , 0
       0                               0
Bank Sta=9913.762,10279.34
Exp/Cntr=0.3,0.1

Type RM Length L Ch R = 1 ,7471.441,145.020100,145.020100,145.020100
XS GIS Cut Line= 6
820219.656203638776731.233578438820295.682632843776817.915812759
820374.826648592776923.374320193820489.306044834777114.321240591
820519.107454453777157.336810784820543.424851384777188.257858991
#Sta/Elev= 30
9719.153442.81429741.931442.84169756.777440.30139786.667433.71499830.675 422.292
9843.335420.67419855.837417.0602 9899.98402.05359905.849399.3675 9916.64393.0899
9930.855383.51679943.357 370.5079949.959364.50899984.925337.01249991.962333.4141
10002.91331.198710014.31335.481510038.22341.670910062.84356.554510073.96365.1189
   10082368.505110097.16370.735810108.76373.767810178.36380.961610214.33386.9067
10234.29392.079510263.97403.540810267.21404.493310276.69405.389410280.84407.3796
#Mann= 3 , 0 , 0
9719.153    0.04       09719.153    0.04       010280.84    0.04       0
#XS Ineff= 2 , 0
       0                               0
Bank Sta=9719.153,10280.84
Exp/Cntr=0.3,0.1

Type RM Length L Ch R = 1 ,7326.421,132.324300,132.324300,132.324300
XS GIS Cut Line= 6
820129.474727733776791.874992336820199.166646233776875.071190817
820242.362878992  776941.0942193820317.458156154777126.373573029
820366.565015763777190.413662464820432.398042449777259.080302743
#Sta/Elev= 30
9718.039411.43149726.397412.70719748.858413.56349762.185411.71989787.629405.1002
 9813.77  396.66 9836.76386.03579863.173376.10669874.999372.42429891.386366.3506
9909.858360.77269920.895359.69619931.932357.50689935.408356.39759942.969353.0753
9954.006345.97619964.724340.00049996.223330.9778 10006.7331.811810017.21336.4308
10027.71339.664610038.21345.086610059.41351.6134 10070.4356.402310092.97365.0564
10104.49365.704710128.77 368.26810227.92375.572410256.82375.885410281.96377.1663
#Mann= 3 , 0 , 0
9718.039    0.04       09718.039    0.04       010281.96    0.04       0
#XS Ineff= 2 , 0
       0                               0
Bank Sta=9718.039,10281.96
Exp/Cntr=0.3,0.1

Type RM Length L Ch R = 1 ,7194.096,146.081100,146.081100,146.081100
XS GIS Cut Line= 6
820119.658901979777069.142894338820138.539752278777077.638541661
820198.259043096  777095.7783637820225.765584335777111.322381926
 820261.54502585777139.852261224820394.373408166777256.948141436
#Sta/Elev= 30
9947.899344.21439953.756343.66369964.721341.01199985.826333.97849996.289 330.006
10001.38331.088310003.38331.415310006.71331.745910017.16336.533110028.34339.8783
10049.76346.897810061.74354.131610068.51358.523410074.43361.828910084.55 363.935
10087.22364.136110100.59364.605410116.16366.058210131.28366.343310146.41367.2302
10166.31368.723510179.64369.8702 10206.3371.493310232.96371.825710237.14371.7771
10246.29371.945610252.26372.204910259.62371.809510272.95372.023310285.45373.6407
#Mann= 3 , 0 , 0
9947.899    0.12       09947.899    0.12       010285.45    0.12       0
#XS Ineff= 2 , 0
       0                               0
Bank Sta=9947.899,10285.45
Exp/Cntr=0.3,0.1

Type RM Length L Ch R = 1 ,7048.015,156.654700,156.654700,156.654700
XS GIS Cut Line= 6
819838.997057782  777074.8011575819935.215899077777136.510229415
820018.297162394777180.382138022 820099.10845536777213.107696723
820125.996447912777226.557603663820218.887251156777250.537406977
#Sta/Elev= 30
9686.725392.50829729.496  393.029753.256392.91769765.136391.56559777.016385.4149
9788.896379.75889800.776377.68389835.186377.65789857.854 376.7969882.897376.9051
9891.337376.11459907.319369.46329923.826361.26429934.615354.06839945.404350.6144
9956.192345.80129966.981340.0202 9977.77336.17669988.809330.325110000.16325.1702
 10008.6329.551910012.29332.165210021.56336.540210031.86339.061910052.45 347.268
10062.75350.487510083.35356.231310096.09358.532110104.16359.367910108.27359.1435
#Mann= 3 , 0 , 0
9686.725    0.12       09686.725    0.12       010108.27    0.12       0
#XS Ineff= 2 , 0
       0                               0
Bank Sta=9686.725,10108.27
Exp/Cntr=0.3,0.1

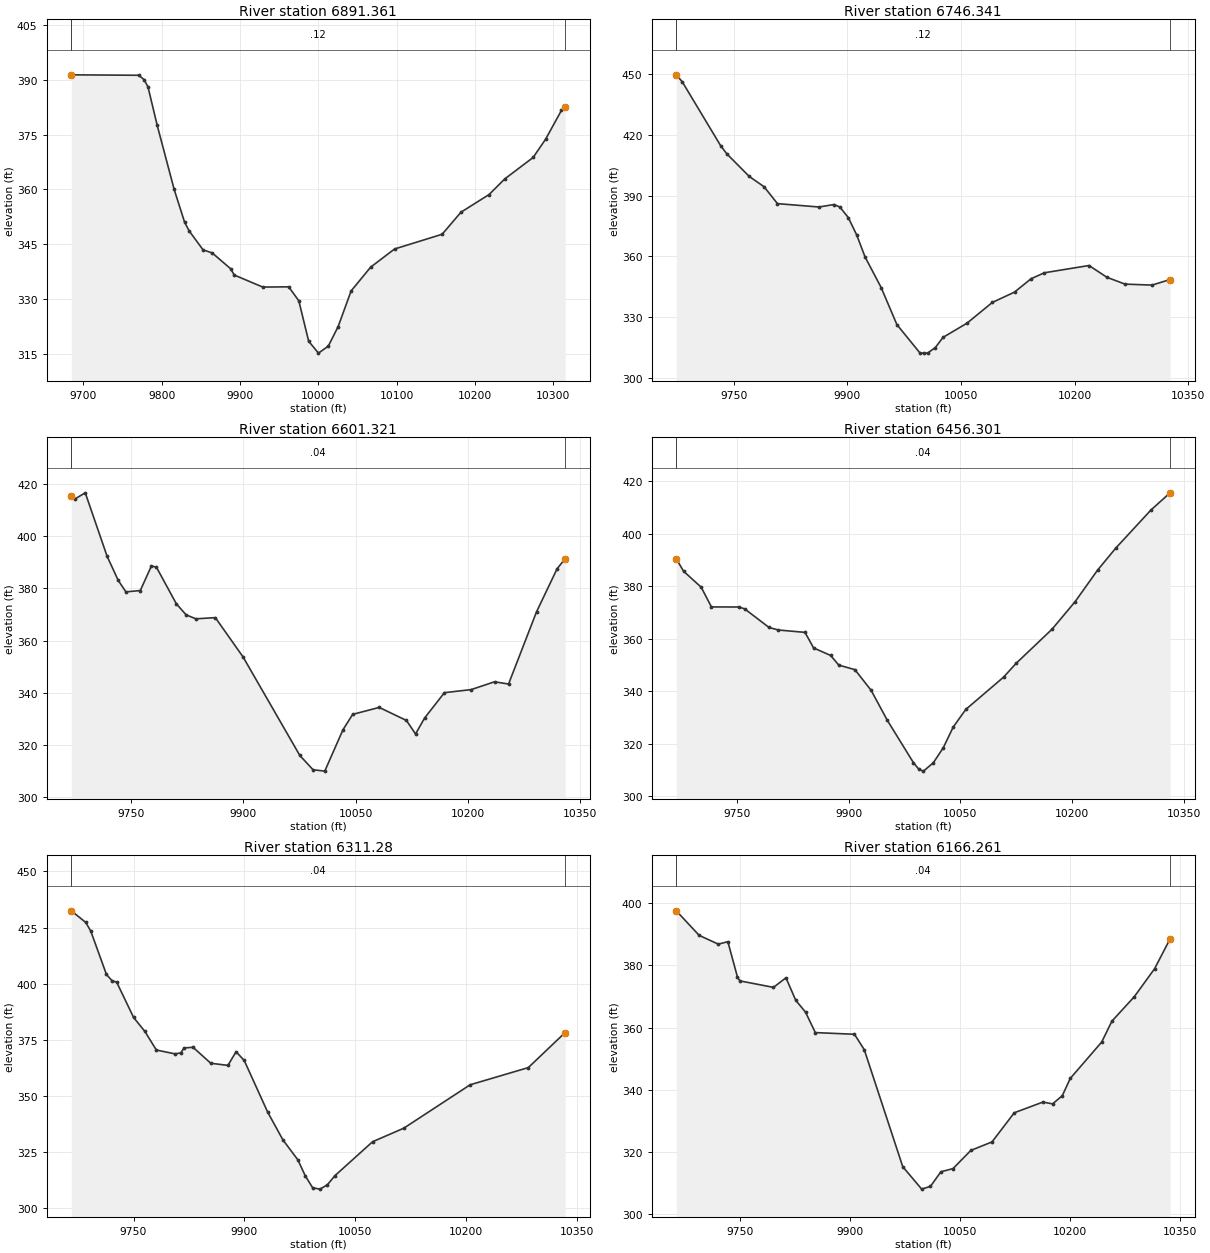
Type RM Length L Ch R = 1 ,6891.361,145.020000,145.020000,145.020000
XS GIS Cut Line= 6
 819822.75598423777174.608351558820038.190252646777310.833595153
820061.737363775777331.913304103820101.850950749777384.662596834
820136.702622599777418.177802604820325.842478183777547.541953933
#Sta/Elev= 30
9684.815391.30199770.925391.17999777.709389.97499782.641 388.0189794.358377.5637
9816.088360.00839829.508350.99919835.277348.68239852.942343.52849864.658342.6763
9888.092338.38719892.845336.64619929.191333.3591  9962.3 333.4289975.226329.6134
9987.805318.569110000.33315.328210012.89317.247910025.46322.589610041.98332.3039
10066.95338.798810097.43343.754110158.21347.7766 10182.2353.789910218.19358.6316
10238.17362.890910274.37368.743510290.17373.683310310.58381.613710315.18  382.55
#Mann= 3 , 0 , 0
9684.815    0.12       09684.815    0.12       010315.18    0.12       0
#XS Ineff= 2 , 0
       0                               0
Bank Sta=9684.815,10315.18
Exp/Cntr=0.3,0.1

Type RM Length L Ch R = 1 ,6746.341,145.020100,145.020100,145.020100
XS GIS Cut Line= 6
819698.681383988 777294.30795113819869.399219884777415.850314478
819930.292825158777442.013265054820004.934931075777455.615488423
820048.254193264777471.607330121820265.054620462 777602.98409084
#Sta/Elev= 30
9673.988449.44669681.961445.95969732.435414.61369740.707410.51949770.291399.4117
9789.896394.31819807.585386.00379862.357384.34099882.116385.55259890.014384.3356
9901.115379.12619912.216 370.5789923.197359.79299944.509 344.6739965.302326.4167
9995.861312.3923   10001312.363210005.95312.383110016.07315.1126 10026.2320.1132
   10058327.148210091.25337.314210120.62342.418710142.42348.990410160.04351.9408
10218.99355.524710242.76349.698710266.53346.357710302.18345.870510326.01348.6082
#Mann= 3 , 0 , 0
9673.988    0.12       09673.988    0.12       010326.01    0.12       0
#XS Ineff= 2 , 0
       0                               0
Bank Sta=9673.988,10326.01
Exp/Cntr=0.3,0.1

Type RM Length L Ch R = 1 ,6601.321,145.020000,145.020000,145.020000
XS GIS Cut Line= 6
819691.315839721777382.699197761819786.210390544 777469.80597577
819842.096050008777516.448119604819946.988293478777588.341818176
820069.302826393777672.309314004820215.561602602777781.357760204
#Sta/Elev= 30
 9670.23415.58939675.231414.37319688.805416.69099717.996392.34879732.784383.1453
9743.102378.6975 9762.36379.21329777.147388.62829783.825388.19529810.491374.1177
9823.516 369.8959836.541368.36219862.592368.81439899.602353.73849975.401315.9666
9993.089310.464210008.76309.938310033.01325.772910046.04331.710610081.52334.3811
10117.89329.367410130.02324.185810142.15330.316610168.59340.034210204.36341.2113
10235.51344.202310254.26343.344610291.68371.066510319.16387.5885 10329.8391.3876
#Mann= 3 , 0 , 0
 9670.23    0.04       0 9670.23    0.04       0 10329.8    0.04       0
#XS Ineff= 2 , 0
       0                               0
Bank Sta=9670.23,10329.8
Exp/Cntr=0.3,0.1

Type RM Length L Ch R = 1 ,6456.301,145.020100,145.020100,145.020100
XS GIS Cut Line= 6
819668.367284832777420.668951319819729.890648619777488.773143878
819767.642720849 777540.23476747819836.777187195777681.062468661
819964.327135003777842.706142653820063.245458019777946.209136251
#Sta/Elev= 30
9669.023390.47169678.713385.75999702.399379.65229716.116372.14569753.303372.1122
9760.825 371.3819793.353364.32219805.755363.35999841.618362.4548 9853.11356.5255
9875.991353.66169886.833349.99719908.519 348.2449930.204340.41099951.889329.0035
9987.069312.79919994.267310.309810000.45309.604110013.77312.825810027.08318.5425
10040.35326.403910057.21333.105810107.79345.379810124.65350.644510172.92363.6775
10203.88374.1776 10233.9386.157310258.46394.594310305.36409.025110331.09415.6036
#Mann= 3 , 0 , 0
9669.023    0.04       09669.023    0.04       010331.09    0.04       0
#XS Ineff= 2 , 0
       0                               0
Bank Sta=9669.023,10331.09
Exp/Cntr=0.3,0.1

Type RM Length L Ch R = 1 , 6311.28,145.020000,145.020000,145.020000
XS GIS Cut Line= 6
819556.633007854777401.008368954819689.120181933 777563.90053024
819712.341648623777624.802543746819740.617601564777801.540676271
819784.092338247777883.987287145819857.747205306777976.144851941
#Sta/Elev= 30
9665.856432.42929685.408427.24229692.151423.39139713.356404.07599720.784401.3643
 9727.33400.56899750.102384.94099765.363 378.7089780.899370.44229805.957368.7265
9813.861369.12399818.438371.35239830.573371.65259854.573364.53519877.817 363.588
9888.832369.67499899.848365.77489931.643 342.7389952.216330.40579972.412321.5337
9982.438 314.4349992.442309.069210002.49308.470810012.51310.443510022.53314.4409
 10073.6329.583610115.83335.610610205.64354.947110284.38362.602510334.17 378.194
#Mann= 3 , 0 , 0
9665.856    0.04       09665.856    0.04       010334.17    0.04       0
#XS Ineff= 2 , 0
       0                               0
Bank Sta=9665.856,10334.17
Exp/Cntr=0.3,0.1

Type RM Length L Ch R = 1 ,6166.261,145.020000,145.020000,145.020000
XS GIS Cut Line= 6
819361.097008035777559.431123056819574.584999987777744.337636615
819654.658751848777811.044579554819686.845177077777844.615902198
819771.885951325777942.615020195 819850.16301056778020.362438271
#Sta/Elev= 30
9663.335397.45849694.512389.57829720.598386.76189733.642387.55339746.685376.2491
9749.888 374.9779795.808372.88459812.871375.96129826.218368.73189839.565364.9273
9852.913358.36899906.302 357.8319919.649 352.8879972.133315.3264 9997.94308.1195
 10009.9309.011710024.17313.6865 10040.7314.715810064.96320.546710093.86 323.278
10124.22332.633410163.23336.066310176.47335.484410189.71338.114610200.51343.6449
10243.46355.352810257.33362.035810287.87369.8873 10315.6378.894110336.62388.4421
#Mann= 3 , 0 , 0
9663.335    0.04       09663.335    0.04       010336.62    0.04       0
#XS Ineff= 2 , 0
       0                               0
Bank Sta=9663.335,10336.62
Exp/Cntr=0.3,0.1

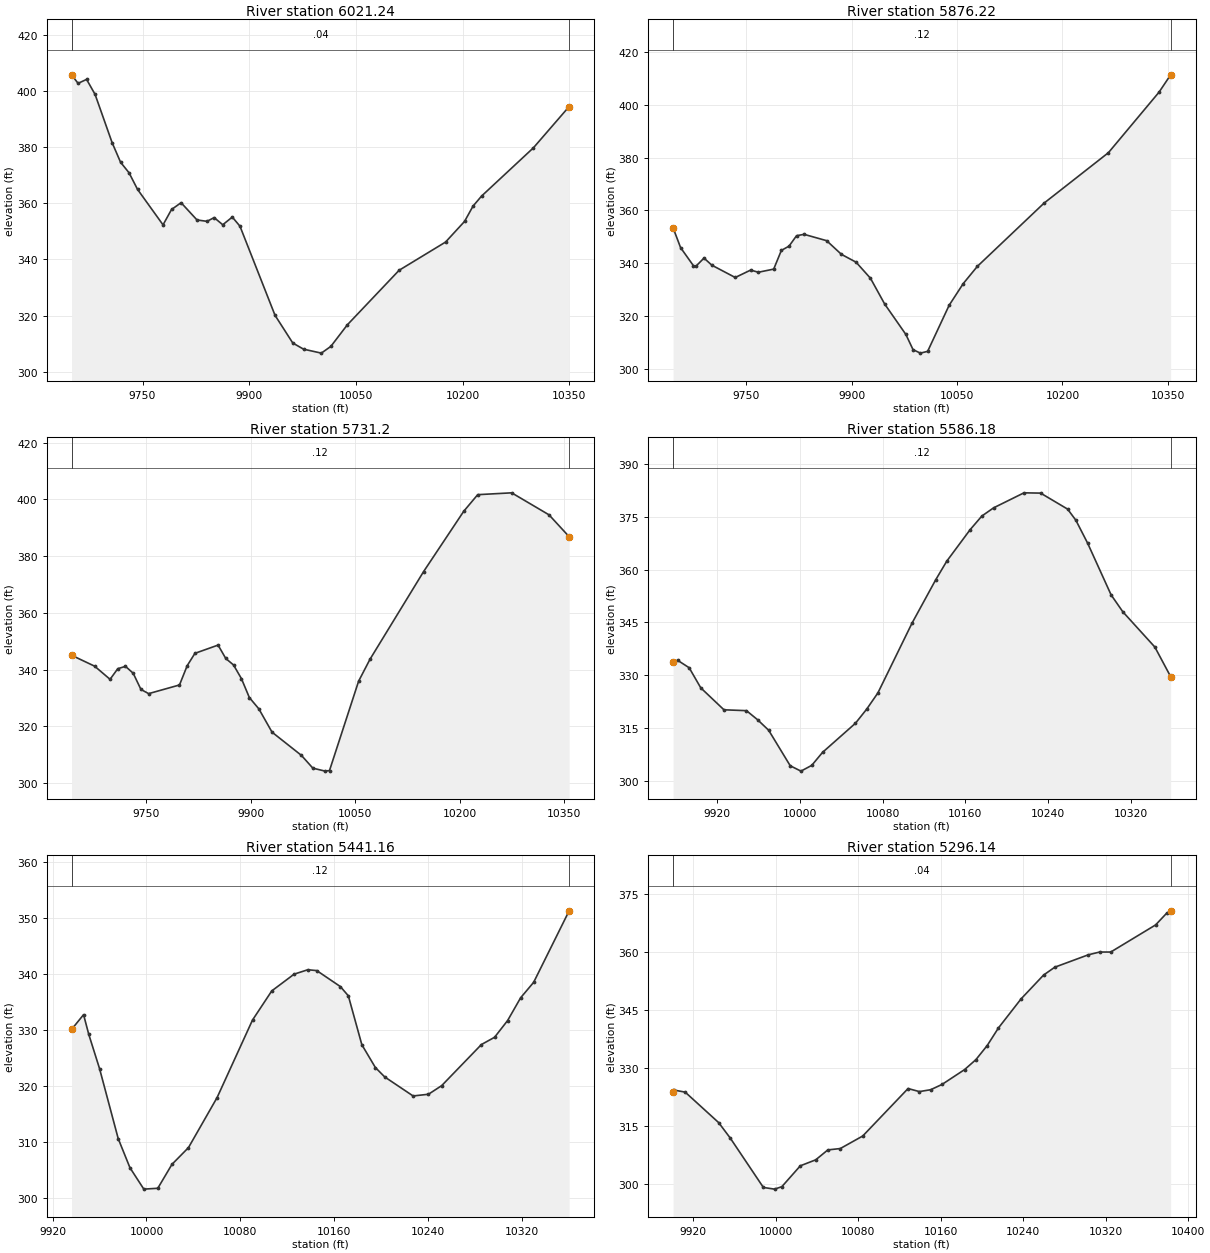
Type RM Length L Ch R = 1 , 6021.24,145.020100,145.020100,145.020100
XS GIS Cut Line= 6
 819227.28801451777680.849781428819444.960506016777824.668071821
819483.629868562777853.969108804819556.477790846777915.251910124
819686.669330948777989.124040377819805.591121248778072.174748441
#Sta/Elev= 30
9650.245405.90279659.453402.86399671.393404.27299683.333398.91359707.213381.7348
9719.153374.70629731.045370.94999743.034365.01269778.854352.35589790.794357.8467
9804.249360.26469826.614354.1035 9840.69353.61529850.697354.94829862.797 352.395
9876.214355.13569886.996351.87819936.291320.07229961.231310.19159976.419307.9891
10001.38306.580610014.78308.992310037.87316.663510110.71336.149810175.99346.2172
10202.69353.5887 10214.6359.045810226.59362.6274 10299.5379.8548 10349.7 394.581
#Mann= 3 , 0 , 0
9650.245    0.04       09650.245    0.04       0 10349.7    0.04       0
#XS Ineff= 2 , 0
       0                               0
Bank Sta=9650.245,10349.7
Exp/Cntr=0.3,0.1

Type RM Length L Ch R = 1 , 5876.22,145.020000,145.020000,145.020000
XS GIS Cut Line= 6
819165.369034426777912.392659293819411.743429265778015.293147756
819463.479870084778020.324332826819551.018521901778003.759919964
819622.783175034778016.680343663819818.694404061778127.884304491
#Sta/Elev= 30
9645.954353.41669656.651345.89699674.924339.04669678.865338.95639689.972341.9397
9701.079339.25129734.399 334.5839756.366 337.3929767.291336.5691 9789.14337.7592
9800.064344.85039810.941346.4608 9821.65350.40779832.359 350.9369864.486348.5267
 9885.48 343.3559906.347340.38069926.847334.28649947.047324.52749977.203313.0009
9987.404307.25039997.807305.923510008.18306.5958 10038.8324.063810058.88332.2853
10078.96338.805310173.73362.736810265.47381.884610337.49404.822710353.98 411.374
#Mann= 3 , 0 , 0
9645.954    0.12       09645.954    0.12       010353.98    0.12       0
#XS Ineff= 2 , 0
       0                               0
Bank Sta=9645.954,10353.98
Exp/Cntr=0.3,0.1

Type RM Length L Ch R = 1 ,  5731.2,145.020000,145.020000,145.020000
XS GIS Cut Line= 6
819125.069547725777947.745025381819374.346356662778068.964031006
819410.228202642778096.737827012819448.142343602  778147.0778744
819486.510492335778179.994216522819726.984181772 778319.09967783
#Sta/Elev= 30
9642.836345.08639675.984341.23249698.134 336.6019709.209340.34579720.284341.1662
9731.358338.73669742.433333.04879753.508331.55319797.808334.60969808.883341.4101
9819.958345.75919853.183348.66199864.258343.94459875.377341.65889886.736336.8375
9898.096330.17419911.716326.19339930.691317.97019972.811 309.797 9989.26305.2893
10006.93304.241910013.16304.456210054.93335.934710071.18343.6281 10148.3374.5944
10205.92395.845410225.92401.681110274.68402.3309 10328.3 394.57210357.17386.8741
#Mann= 3 , 0 , 0
9642.836    0.12       09642.836    0.12       010357.17    0.12       0
#XS Ineff= 2 , 0
       0                               0
Bank Sta=9642.836,10357.17
Exp/Cntr=0.3,0.1

Type RM Length L Ch R = 1 , 5586.18,145.020100,145.020100,145.020100
XS GIS Cut Line= 6
819271.116969082778209.059152085819321.398944566778234.513148727
819356.390471511778248.127984551819423.663139184 778267.89240239
819474.299056365778289.187921386819705.684303833778412.249441826
#Sta/Elev= 30
9877.424333.80199881.776334.23469892.984332.10449904.192326.39399926.609320.1494
9948.376 319.9059959.106317.33099969.836314.33749990.685304.239610001.06302.7138
 10011.5304.354710021.95308.053110053.75316.3279 10064.6320.333710075.45324.9507
10108.39344.761510131.28357.083310142.04 362.416 10164.6371.353410175.95375.2383
10187.31377.567710216.67381.833810232.75381.754210258.84377.203310266.82374.0438
10278.18367.5325 10300.9352.819510312.26348.002510343.18 337.99210358.47329.5731
#Mann= 3 , 0 , 0
9877.424    0.12       09877.424    0.12       010358.47    0.12       0
#XS Ineff= 2 , 0
       0                               0
Bank Sta=9877.424,10358.47
Exp/Cntr=0.3,0.1

Type RM Length L Ch R = 1 , 5441.16,145.020000,145.020000,145.020000
XS GIS Cut Line= 6
819247.145413434778308.666631244819277.815113662778340.162835895
819301.626205289778376.733449253 819329.49405732778400.101321185
819451.943250409778473.786935393819592.180417354778544.918736598
#Sta/Elev= 30
9936.098330.13259946.351332.77639950.795329.24629959.971323.14459975.911310.6199
9985.898305.43499997.735 301.60410009.66301.757710021.73306.030310035.82309.0223
10060.26 317.97610090.43331.814510106.86337.023810125.92340.0158 10137.6340.8047
10145.22340.652610165.36337.797410172.16336.145110183.68327.4068 10195.2323.3348
 10203.2321.649310227.39318.250710240.51318.5584 10251.8320.103510285.65 327.441
10296.85328.733710307.98331.7238 10319.1335.795510330.23338.565810360.46351.3317
#Mann= 3 , 0 , 0
9936.098    0.12       09936.098    0.12       010360.46    0.12       0
#XS Ineff= 2 , 0
       0                               0
Bank Sta=9936.098,10360.46
Exp/Cntr=0.3,0.1

Type RM Length L Ch R = 1 , 5296.14,145.020100,145.020100,145.020100
XS GIS Cut Line= 6
819154.126680092 778437.29403694 819195.44757254778454.147018917
819224.623715656778469.390671109819280.480240349778507.015572254
819317.939782187778526.625826592819588.482551769778644.553805727
#Sta/Elev= 30
9900.664323.91579901.607324.32389912.407323.79089944.806315.90559956.067311.9002
9988.206299.0926    9999  298.6610006.09299.291910024.02304.704210038.95 306.252
10050.66308.819710062.77309.175710084.52312.426110128.44 324.718 10139.4323.9323
10150.35324.415610161.31325.776710183.22329.629110194.18332.201410205.14335.8565
10216.09340.435610238.01347.957610259.81 354.12310270.67356.160810303.23359.3791
10314.08360.086610324.93360.091710368.35367.1097 10379.2370.177110382.98370.7662
#Mann= 3 , 0 , 0
9900.664    0.04       09900.664    0.04       010382.98    0.04       0
#XS Ineff= 2 , 0
       0                               0
Bank Sta=9900.664,10382.98
Exp/Cntr=0.3,0.1

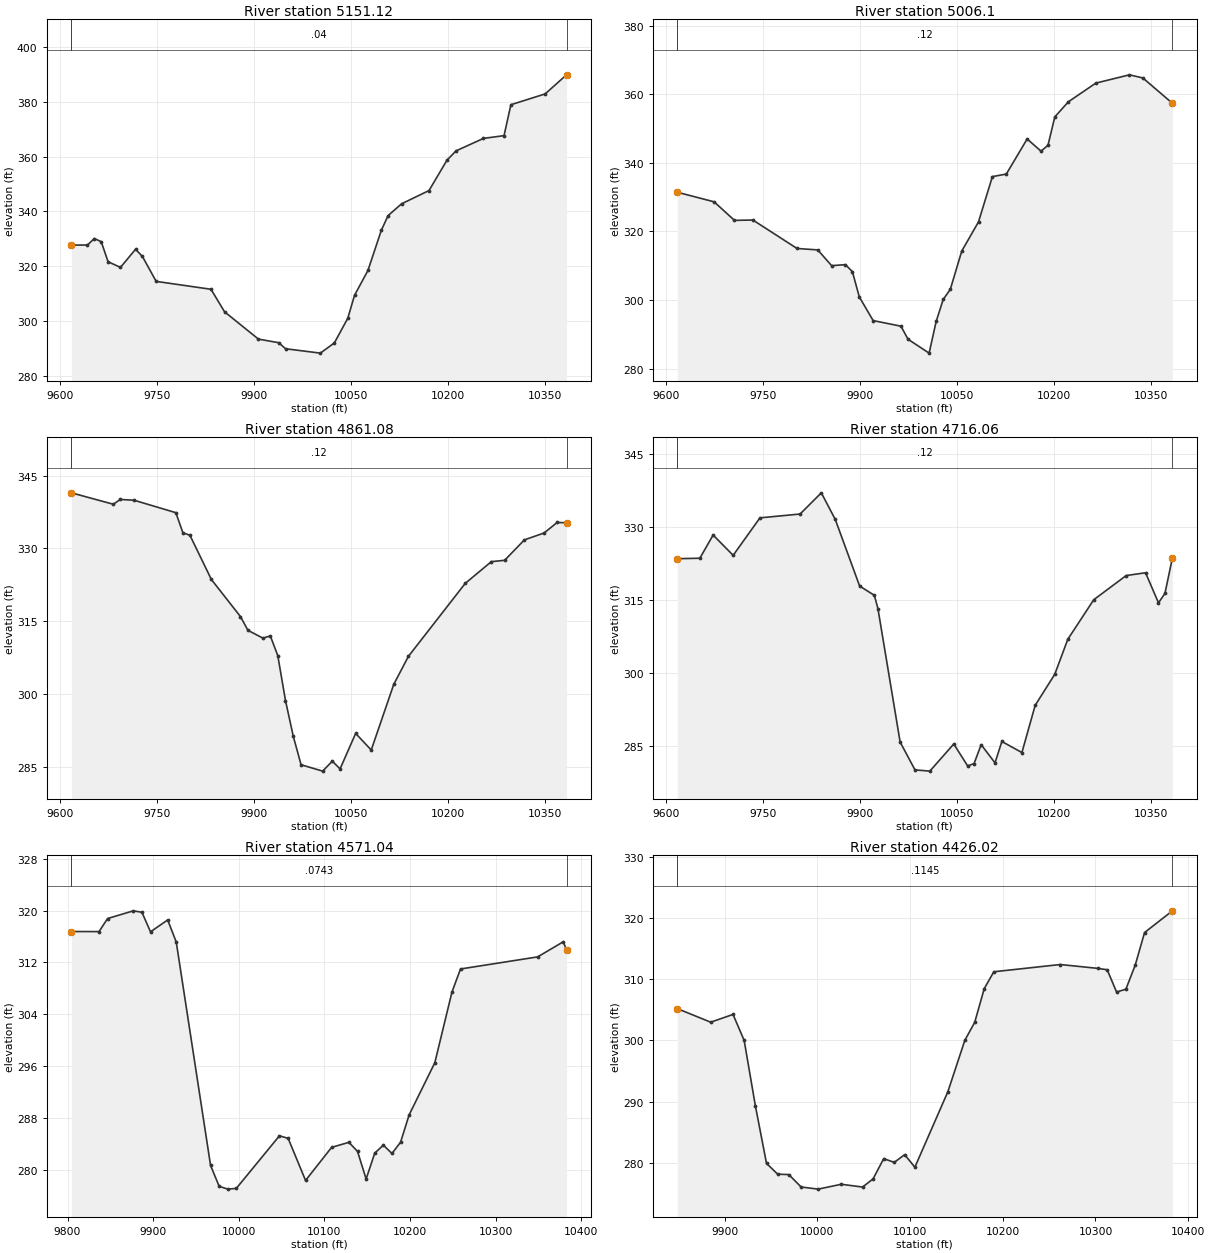
Type RM Length L Ch R = 1 , 5151.12,145.020000,145.020000,145.020000
XS GIS Cut Line= 6
818831.617153975  778489.3376931819020.322906251 778557.17000771
 819158.54316605778600.847808409819217.198462966778625.554201471
819355.576120218778665.733756038819556.159304407778736.599382701
#Sta/Elev= 30
9617.013327.69179641.861327.74349652.487 330.1099663.114328.9532 9673.74321.6195
9692.877319.54669716.246326.18739726.872323.53979748.125314.43199832.933311.5482
9853.908303.31269906.345293.31489937.807291.99969948.294289.790210002.11288.1899
10023.77291.907710044.62300.9641   10055309.328610075.76318.433710096.51333.1399
10106.89338.486410127.75342.803910170.26347.667210198.07358.780510212.07362.1757
10254.49366.736210286.31367.742610296.91379.049810349.94383.010910382.99389.9887
#Mann= 3 , 0 , 0
9617.013    0.04       09617.013    0.04       010382.99    0.04       0
#XS Ineff= 2 , 0
       0                               0
Bank Sta=9617.013,10382.99
Exp/Cntr=0.3,0.1

Type RM Length L Ch R = 1 ,  5006.1,145.020000,145.020000,145.020000
XS GIS Cut Line= 6
818811.509618815 778614.56529116819122.957167072778732.361667159
819242.135355103778784.180696856819341.805394651778823.602168713
819423.478245953778851.705905815819528.945730028778881.148959219
#Sta/Elev= 30
9616.983331.42759673.951328.62759705.451323.21589733.965323.31829802.213315.0268
9834.344314.60019855.765310.00749877.186310.30689887.896308.26429898.607300.8942
9920.028293.99429963.066292.3593 9973.94 288.55810006.61 284.50410017.53293.7596
10028.45300.172210039.37303.097710057.09314.262110083.01322.778210104.52335.9804
10126.03336.719110158.29346.953910179.79343.393910190.49345.112710201.07353.3895
10222.14357.811710264.52363.244910316.59365.660710337.36364.740810382.99357.3727
#Mann= 3 , 0 , 0
9616.983    0.12       09616.983    0.12       010382.99    0.12       0
#XS Ineff= 2 , 0
       0                               0
Bank Sta=9616.983,10382.99
Exp/Cntr=0.3,0.1

Type RM Length L Ch R = 1 , 4861.08,145.020100,145.020100,145.020100
XS GIS Cut Line= 6
818743.630385371778707.808261803818972.071317649778799.988921407
819160.832384117778920.822038152819233.702531757 778959.18204097
819331.681585707778991.676286762819439.368758404779010.518688189
#Sta/Elev= 30
9617.019341.43219681.867339.07779692.551 340.066 9713.95339.90569778.575337.3418
9789.451333.21049800.327332.69179833.522323.57939878.541315.93659890.088313.1042
9913.182311.5006 9924.73311.94819936.277 307.8899948.184298.63449960.246291.2632
9972.307285.408810005.71284.097410020.59  286.1510032.64284.561110056.73291.8721
10080.83288.443310115.72301.988610138.38307.748810226.27322.778310266.64327.2568
10287.18 327.528 10317.8331.740810348.24333.158610368.44335.321710382.95335.2666
#Mann= 3 , 0 , 0
9617.019    0.12       09617.019    0.12       010382.95    0.12       0
#XS Ineff= 2 , 0
       0                               0
Bank Sta=9617.019,10382.95
Exp/Cntr=0.3,0.1

Type RM Length L Ch R = 1 , 4716.06,145.020000,145.020000,145.020000
XS GIS Cut Line= 6
818651.025207123778860.518354908818874.686907737778925.466702831
819065.971075323779025.587619353819123.563709302779048.084100575
 819220.05952666779065.280259204 819376.50685773779073.259231026
#Sta/Elev= 30
9617.003 323.5119651.893323.60369672.431328.38929703.444324.20299744.889331.9265
9807.009332.72129839.806337.08799861.355331.61649899.113317.87169921.839315.9618
 9927.41313.22499961.758285.71449984.721279.976410007.69279.720610044.75285.3161
10066.25 280.78510076.15281.283510087.11285.172710108.56281.422310119.12285.8323
10150.15283.550210170.67293.280710200.96299.677810221.15306.8989 10261.3315.0495
10311.42320.034310341.43320.612110361.44314.407710371.44316.359210382.95323.6592
#Mann= 3 , 0 , 0
9617.003    0.12       09617.003    0.12       010382.95    0.12       0
#XS Ineff= 2 , 0
       0                               0
Bank Sta=9617.003,10382.95
Exp/Cntr=0.3,0.1

Type RM Length L Ch R = 1 , 4571.04,145.020100,145.020100,145.020100
XS GIS Cut Line= 6
818762.847134552 779137.64706055818919.732039944779126.132599383
818979.612252484779123.198209987819072.929508786779106.545345224
819143.102390039779099.046320053819338.768057577779091.882833969
#Sta/Elev= 30
9804.534316.77659836.773 316.763  9846.8318.78299876.881319.97359886.907319.7489
9896.934316.73079916.988318.56659927.015 315.1469967.115280.62169977.126 277.409
9987.138276.96959997.149277.081310047.58285.211110057.74284.811910078.06278.3112
10108.53283.423710128.72284.200110138.78282.798810148.84278.534410158.89 282.533
10168.95283.769210179.01 282.47610189.06284.219310199.06288.439710229.08296.4988
 10249.1 307.421 10259.1310.988510349.16 312.85310379.18315.193310382.95313.8889
#Mann= 3 , 0 , 0
9804.534  0.0743       09804.534  0.0743       010382.95  0.0743       0
#XS Ineff= 2 , 0
       0                               0
Bank Sta=9804.534,10382.95
Exp/Cntr=0.3,0.1

Type RM Length L Ch R = 1 , 4426.02,145.020000,145.020000,145.020000
XS GIS Cut Line= 6
818913.622337741779306.924981776819026.680955467779234.586761708
819155.785181385779169.230809438819195.459482722779155.186682959
819249.763984559779141.436811688819404.779294204779118.917071356
#Sta/Elev= 30
9849.064305.19239885.114302.97419909.175304.24249921.206299.98459933.237289.3406
9945.268 279.9179957.298278.14439969.329278.07579982.639276.0502   10001275.7023
10025.93276.495410048.87276.041810060.21277.379110071.64280.679610083.06280.0765
10094.25281.331110105.27279.284310140.84291.616910159.16300.019110169.77302.9422
10180.09 308.46610190.41311.211710262.02312.396310302.59311.766410312.66311.5415
10322.74307.906810332.81308.359110342.89312.305310352.96317.619710382.96321.1676
#Mann= 3 , 0 , 0
9849.064  0.1145       09849.064  0.1145       010382.96  0.1145       0
#XS Ineff= 2 , 0
       0                               0
Bank Sta=9849.064,10382.96
Exp/Cntr=0.3,0.1

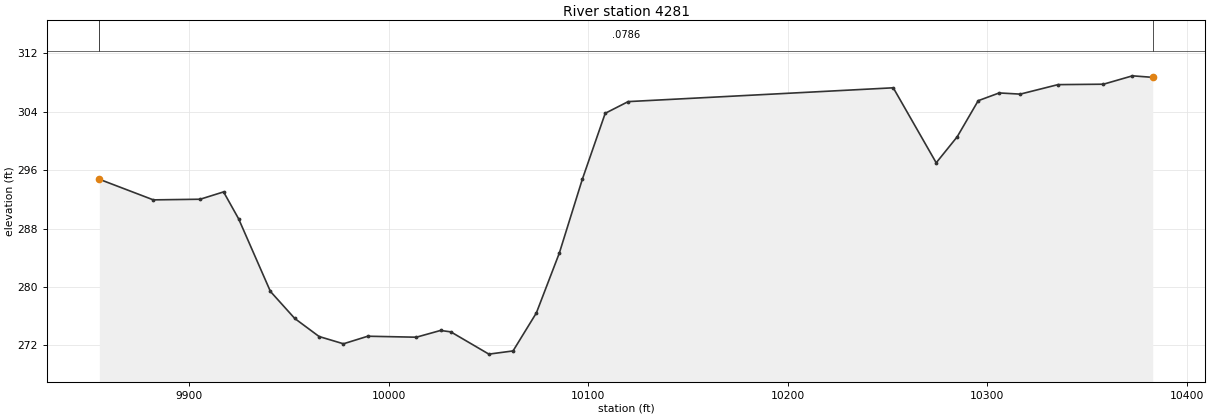
Type RM Length L Ch R = 1 ,    4281,0.000000,0.000000,0.000000
XS GIS Cut Line= 6
 818991.91617676779431.517161955 819064.42118621779387.018654266
819168.302697352779315.121286406819245.337517856779271.346484036
 819354.21626701779224.161082337819458.811740794779192.280896509
#Sta/Elev= 30
9854.842294.75329881.926 291.9289905.393292.01639917.126293.02089924.654289.3403
9940.619 279.374 9952.82 275.6689965.021273.19489977.223272.19689989.424273.2352
10013.77273.100510025.89274.024910031.06273.832810050.13270.780610062.25271.2185
10073.95 276.43110085.46284.637910096.96294.733910108.46303.796410119.96305.4001
10252.87307.2935 10274.4297.011710284.93300.579110295.46305.526110305.99306.5891
10316.52306.425710335.43307.727310358.24307.7862 10372.8308.934810382.96308.7249
#Mann= 3 , 0 , 0
9854.842  0.0786       09854.842  0.0786       010382.96  0.0786       0
#XS Ineff= 2 , 0
       0                               0
Bank Sta=9854.842,10382.96
Exp/Cntr=0.3,0.1